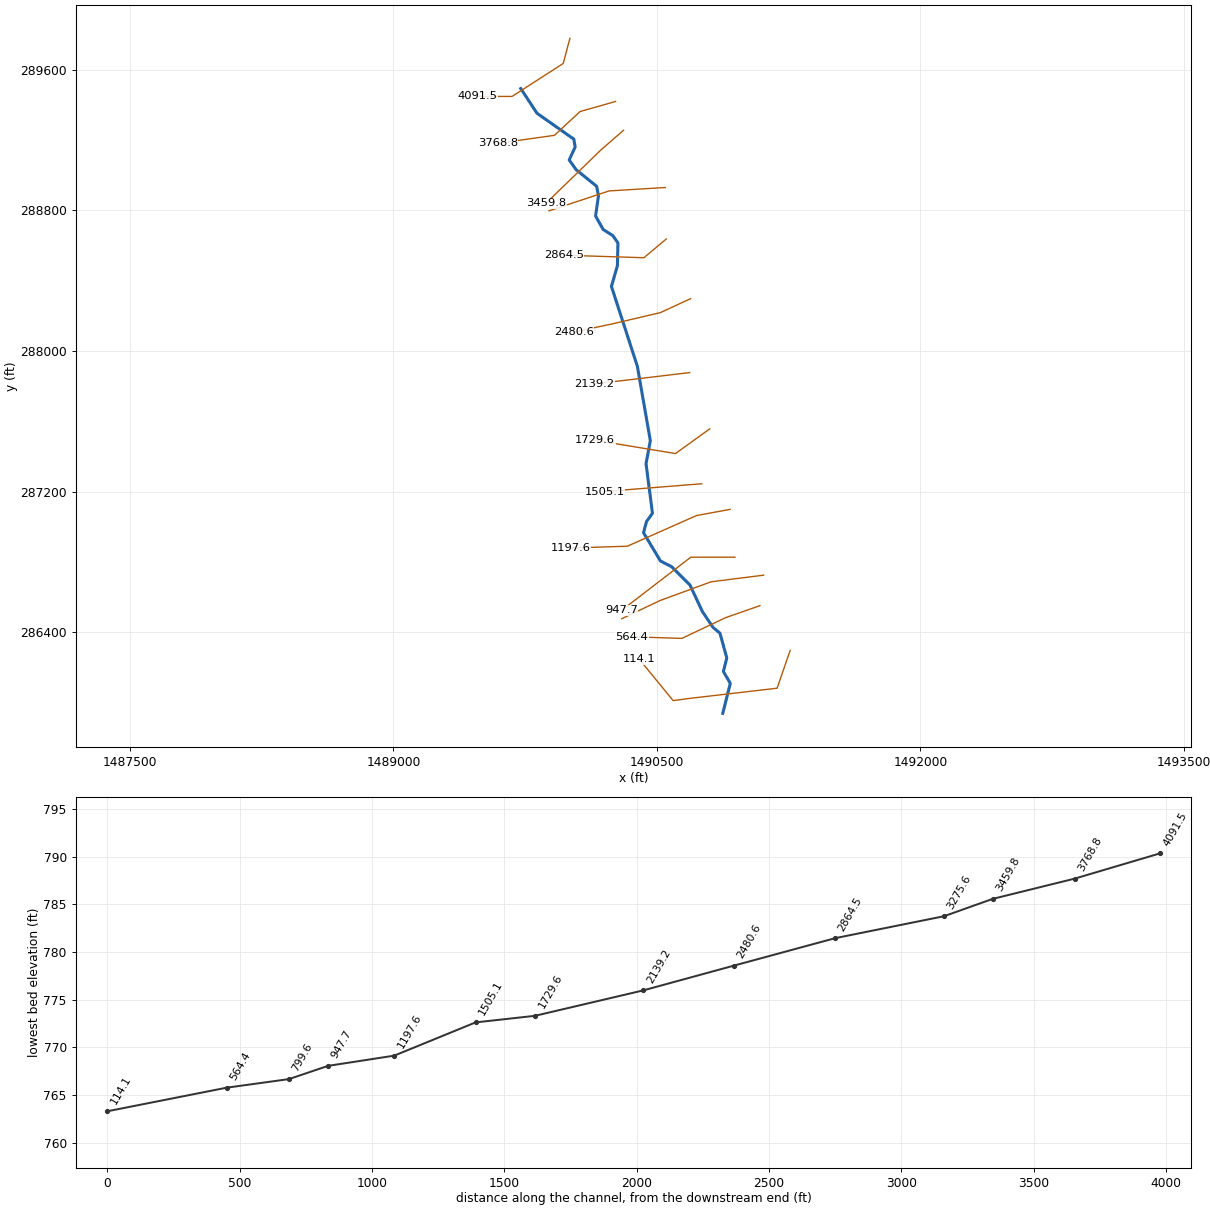
--- LYFLDSRN.prj (project) ---

Proj Title=LYFLDSRN
Current Plan=p01
Default Exp/Contr=0,0
English Units
Geom File=g01
Flow File=f01
Plan File=p01
BEGIN DESCRIPTION:
END DESCRIPTION:
DSS Export Rating Curves= 0
DSS Export Rating Curve Sorted= 0
DSS Export Volume Flow Curves= 0
DXF OffsetX= 0
DXF OffsetY= 0
DXF ScaleX= 0
DXF ScaleY= 0

--- LYFLDSRN.p01 (plan) ---

Plan Title=Floodplain
Program Version=4.00
Geom File=g01
Flow File=f01
K Sum by GR=0
Std Step Tol=0.01
Critical Tol=0.01
Num of Std Step Trials=20
Max Error Tol=0.3
Flow Tol Ratio=0.001
Split Flow NTrial=30
Split Flow Tol=0.02
Split Flow Ratio=0.02
Log Output Level=0
Friction Slope Method=1
Unsteady Friction Slope Method=2
Unsteady Bridges Friction Slope Method=1
Global Log Level=0
CheckData=False
Run HTab=0
Run UNet=0
Run PostProcess=0
UNET Theta=0
UNET Theta Warmup=0
UNET ZTol=0
UNET ZSATol=0
UNET MxIter=0
UNET MaxInSteps=0
UNET DtIC=0
UNET DtMin=0
UNET MaxCRTS=0
UNET WFStab=0
UNET SFStab=0
UNET WFX=0
UNET SFX=0
UNET DSS MLevel=0
UNET DZMax Abort=0
UNET Convert EG Bridges=0
UNET Use Existing IB Tables=0
UNET Froude Limit=0
UNET Froude Power=0
Write IC File=0
Echo Input=False
Echo Output=False
Write Detailed=0

--- LYFLDSRN.f01 (steady flow) ---

Flow Title=NFF Regression Equation
Program Version=4.10
Number of Profiles= 1
Profile Names=P100yr
River Rch & RM=LYFLDSRN,Main            ,4091.5
922.8624
River Rch & RM=LYFLDSRN,Main            ,799.6
994.3848
River Rch & RM=LYFLDSRN,Main            ,564.4
997.9828
Boundary for River Rch & Prof#=LYFLDSRN,Main            , 1
Up Type= 0
Dn Type= 3
Dn Slope=0.006
DSS Import GetInterval= 0
DSS Import GetPeak= 0
DSS Import FillOption= 0

--- LYFLDSRN.g01 (geometry) ---

Geom Title=USGS 10m DEM
Program Version=4.10

River Reach=LYFLDSRN        ,Main
Reach XY= 30
      1489725.17      289493.693     1489817.355      289353.183
     1490027.299       289205.78     1490034.425      289160.699
     1490000.633      289087.625     1490039.513      289032.603
     1490156.944      288937.386     1490167.305      288882.656
     1490150.778      288768.012     1490194.181      288691.623
     1490248.868        288656.9     1490278.169      288614.859
     1490274.967      288485.026     1490241.055      288367.838
     1490388.655      287912.871     1490462.481      287489.862
     1490437.992      287358.719     1490474.637      287076.075
     1490440.926      287030.053     1490423.586      286966.134
     1490520.088      286804.808     1490583.181      286772.599
     1490688.201      286667.908     1490758.198      286518.073
     1490818.747        286427.3     1490858.721      286393.831
     1490897.611      286253.988     1490878.273      286176.213
     1490917.674      286108.175     1490874.629       285937.53

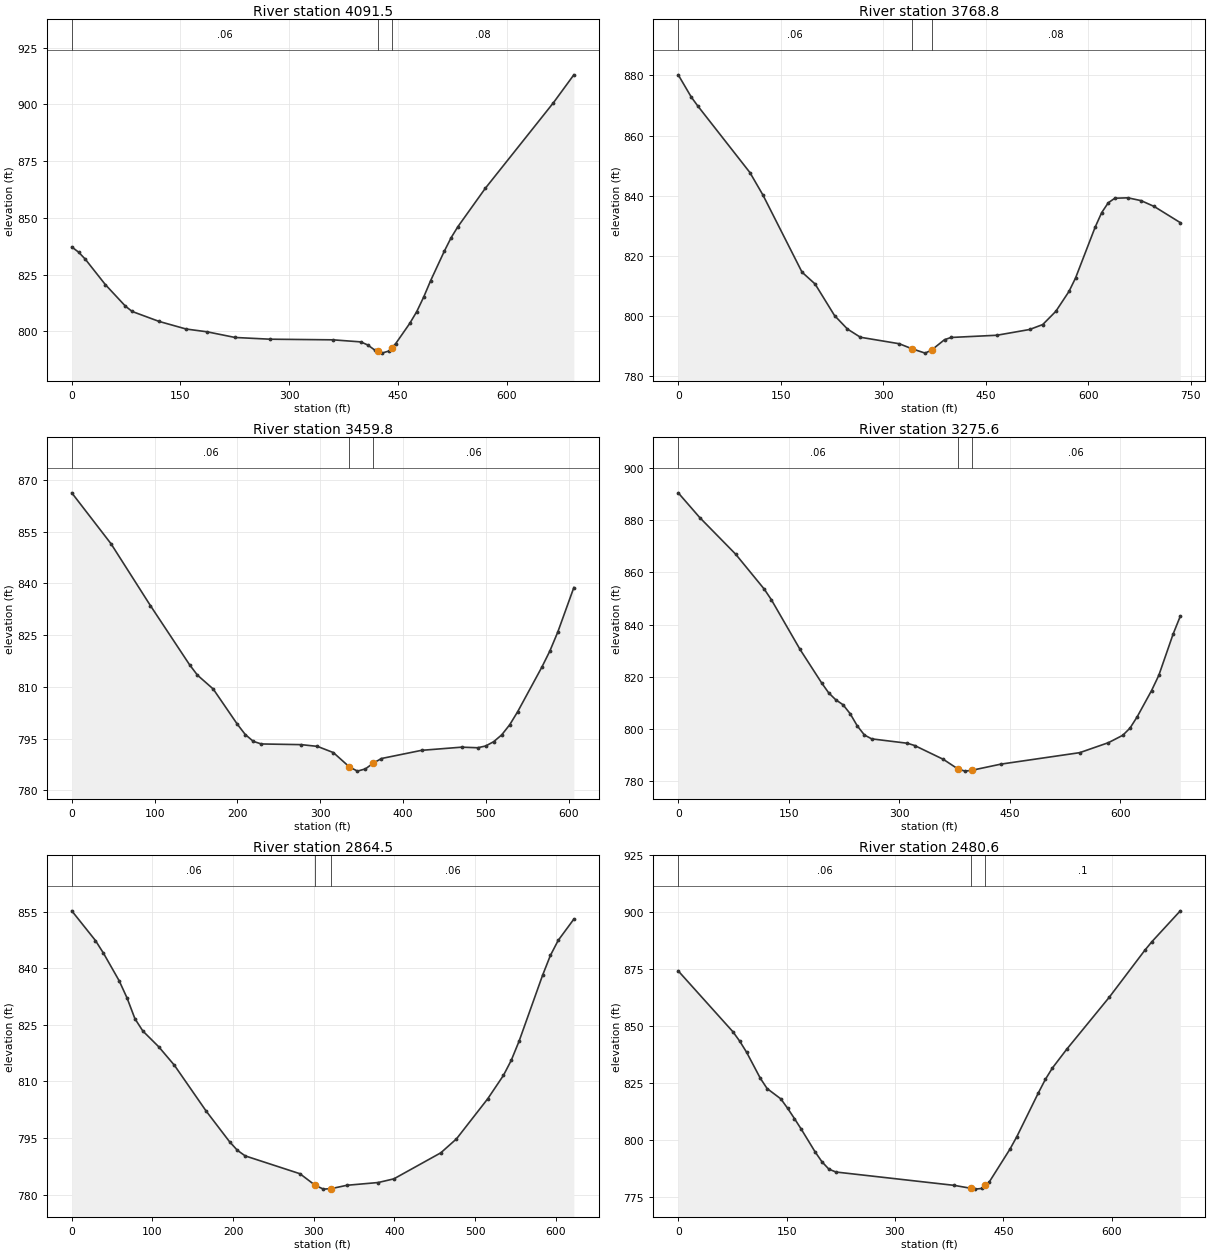
Type RM Length L Ch R = 1 ,4091.5  ,318.7,322.7,326.6
XS GIS Cut Line= 4
     1490004.606      289779.633     1489966.628      289636.404
     1489674.745      289448.687     1489477.262      289449.772
#Sta/Elev= 30
       0  837.15     9.3  834.88    18.5  831.82    46.3  820.56    74.1  811.03
    83.4   808.7   120.4  804.33   157.8  800.97   186.7  799.75   225.3  797.25
   273.5  796.49   360.3  796.21   398.8   795.3   408.5  793.92   418.1  791.68
  422.27791.1032   427.7  790.35   437.4  791.26  441.39 792.644     447  794.59
   466.3  803.45   475.9  808.62   485.6  815.11   495.2  822.36     514  835.29
   523.4  841.24   532.8  846.12   570.4  862.93   664.5   900.7   692.7  913.01
#Mann= 3 , 0 , 0
       0     .06       0  422.27    .045       0  441.39     .08       0
Bank Sta=422.27,441.39
XS Rating Curve= 0 ,0
Exp/Cntr=0.3,0.1

Type RM Length L Ch R = 1 ,3768.8  ,307,309.1,310.4
XS GIS Cut Line= 4
     1490264.371      289420.258     1490062.548      289362.966
     1489916.715      289227.549     1489593.798      289181.976
#Sta/Elev= 30
       0  880.16    19.1  872.77    28.6  869.82   104.9   847.7     124  840.22
   181.2   814.6   200.3  810.67   228.8  800.18   247.7   795.7   266.7  792.97
   323.5  790.82   342.5  789.12   361.4   787.7   370.9  788.74   389.8  792.17
   399.3   792.9   466.4  793.64   514.3  795.55   533.5  797.19   552.7  801.59
   571.9  808.18   581.5  812.63   610.2  829.52   619.8  834.38   629.4  837.64
     639  839.16   658.2   839.3   677.4  838.37   696.6  836.43   734.9  831.05
#Mann= 3 , 0 , 0
       0     .06       0   342.5    .045       0   370.9     .08       0
Bank Sta=342.5,370.9
XS Rating Curve= 0 ,0
Exp/Cntr=0.3,0.1

Type RM Length L Ch R = 1 ,3459.8  ,195.8,184.1,172.3
XS GIS Cut Line= 3
     1490309.944      289256.195     1490181.038      289144.216
     1489868.538      288840.831
#Sta/Elev= 30
       0  866.29    47.4  851.52    94.9  833.61   142.3  816.42   151.8  813.41
   170.8   809.4   199.8  799.23   209.5   796.2   219.2  794.22   228.8  793.46
   277.2  793.26   296.6  792.76   315.9  790.96   335.3  786.79     345  785.58
   354.6  786.23   364.3  787.93     374  789.24   422.4  791.61   470.8  792.53
   490.2  792.36   499.8  792.87   509.5  794.12   519.2   796.1   528.9  799.05
   538.5  802.83   567.6  815.71   577.3   820.4   586.9  825.91   606.3  838.83
#Mann= 3 , 0 , 0
       0     .06       0   335.3    .045       0   364.3     .06       0
Bank Sta=335.3,364.3
XS Rating Curve= 0 ,0
Exp/Cntr=0.3,0.1

Type RM Length L Ch R = 1 ,3275.6  ,419.4,411.1,401.1
XS GIS Cut Line= 3
     1490548.226      288930.674     1490227.913      288911.143
     1489885.465      288797.862
#Sta/Elev= 30
       0  890.54    29.2  881.05    77.8  867.05   116.7  853.62   126.4  849.54
   165.3  830.49   194.5  817.69   204.2  813.81   213.9  811.12   223.7  809.24
   233.4   805.8   243.1   801.1   252.8  797.61   262.6  796.14   311.2  794.45
   320.9  793.59   359.9  788.28   379.4  784.65   389.2  783.76   398.9   784.1
   437.9  786.44   545.1  790.85   584.1  794.69   603.6  797.53   613.4  800.31
   623.1  804.63   642.6  814.69   652.4  820.51   671.9   836.4   681.6  843.23
#Mann= 3 , 0 , 0
       0     .06       0   379.4    .045       0   398.9     .06       0
Bank Sta=379.4,398.9
XS Rating Curve= 0 ,0
Exp/Cntr=0.3,0.1

Type RM Length L Ch R = 1 ,2864.5  ,376.7,383.9,390.5
XS GIS Cut Line= 3
     1490553.434      288637.706      1490425.83      288530.935
     1489970.101      288545.258
#Sta/Elev= 30
       0  855.19    29.4  847.31    39.2     844    58.7  836.68    68.5  832.11
    78.3   826.6    88.1  823.35   107.7  819.19   127.2  814.28   166.4  802.19
   195.5  794.04   205.2  791.76   214.9  790.27   282.8  785.54   301.7782.4777
   311.9  781.46   321.7781.5954     341  782.48   379.8  783.21   399.2  784.18
   457.4  791.08   476.8  794.77   515.6  805.41     535  811.58   544.7  815.58
   554.4  820.64   583.5  838.09   593.2  843.36   602.9  847.36   622.3  852.99
#Mann= 3 , 0 , 0
       0     .06       0   301.7    .045       0   321.7     .06       0
Bank Sta=301.7,321.7
XS Rating Curve= 0 ,0
Exp/Cntr=0.3,0.1

Type RM Length L Ch R = 1 ,2480.6  ,344.2,341.4,338.7
XS GIS Cut Line= 4
     1490691.455      288297.862      1490519.58      288218.435
     1490247.444      288154.633      1490026.09      288107.758
#Sta/Elev= 30
       0  874.32    75.7  847.62    85.2  843.46    94.7  838.59   113.6  827.24
   123.1  822.68     142  818.18   151.5  814.02   160.9  809.52   170.4  804.84
   189.3  795.02     199  790.56   208.6  787.33   218.3  786.08   382.1  780.22
   405.3778.9263     411  778.57   420.7  778.88   425.3780.1666   430.3  781.56
   459.2  796.09   468.8  801.61   498.4  820.69   508.2  826.68     518  831.71
   537.7  839.89   596.7  862.75   645.9  883.35   655.8  887.15   695.1  900.68
#Mann= 3 , 0 , 0
       0     .06       0   405.3    .045       0   425.3      .1       0
Bank Sta=405.3,425.3
XS Rating Curve= 0 ,0
Exp/Cntr=0.3,0.1

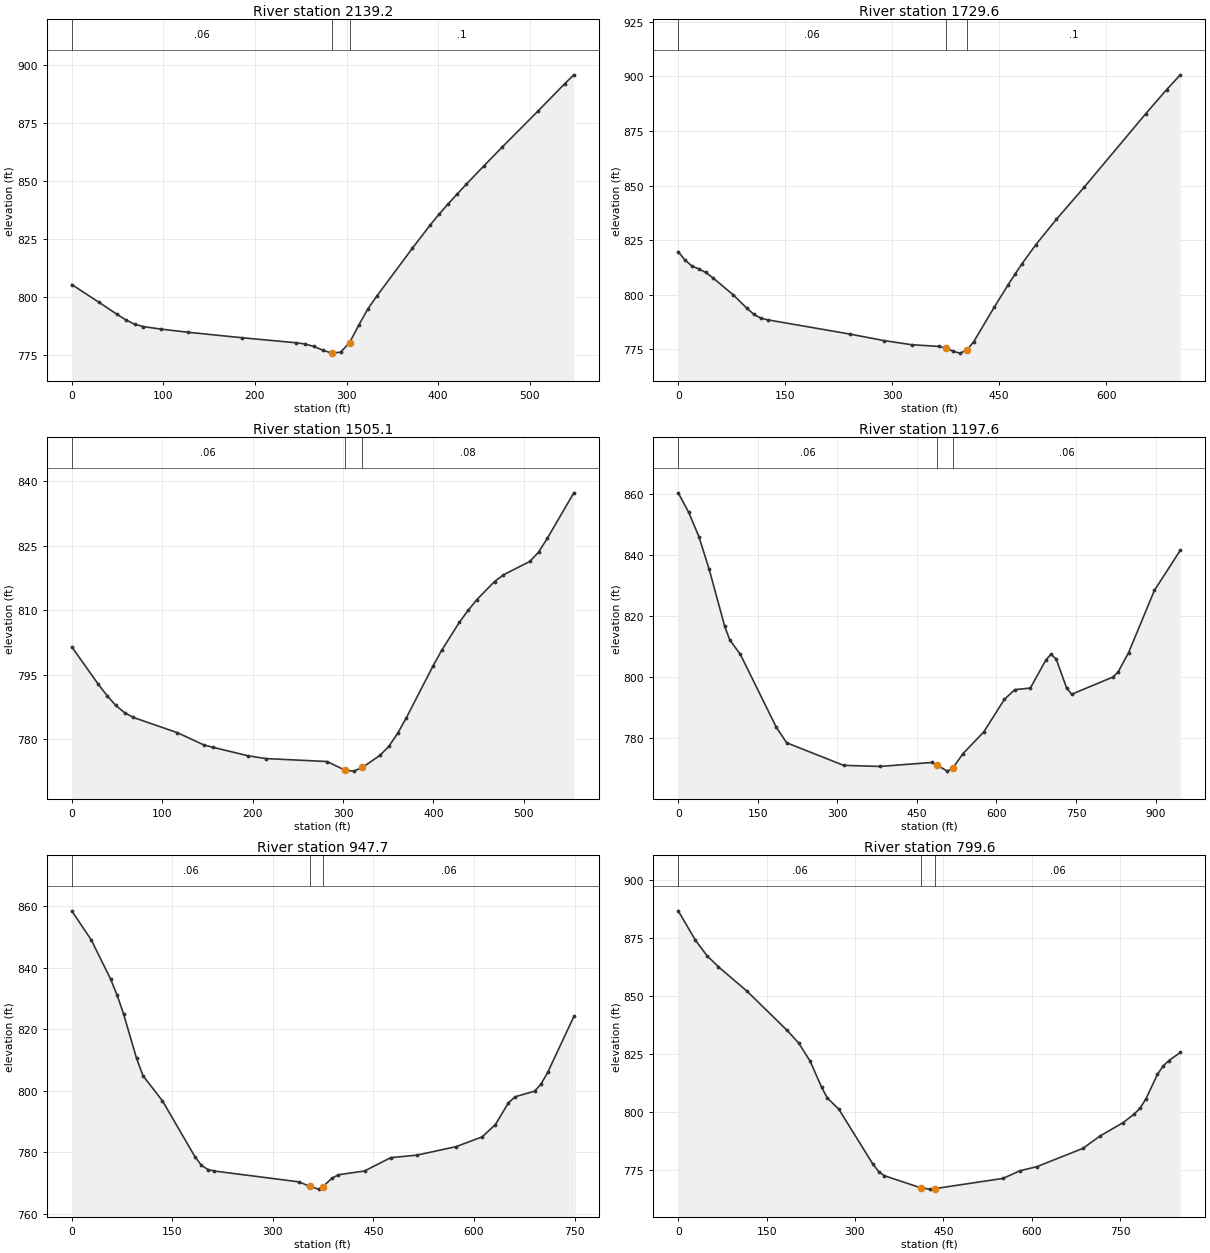
Type RM Length L Ch R = 1 ,2139.2  ,416.8,409.6,402.5
XS GIS Cut Line= 2
     1490686.246      287877.289     1490141.976      287812.185
#Sta/Elev= 30
       0  805.51    29.4  797.94    48.9  792.82    58.7  790.37    68.5  788.44
    78.3  787.38    97.9   786.3   127.2  784.95     186   782.6   244.7  780.45
   254.5  779.92   264.3  778.86   274.1  777.26   283.9  775.98   293.6  776.41
   303.4  780.53   313.2  787.93     323  794.81   332.8  800.39     372  821.19
   391.5  831.19   401.3  835.89   411.1  840.29   420.9   844.5   430.7  848.64
   450.3  856.71   469.8  864.62     509  880.16   538.4  892.02   548.2  895.78
#Mann= 3 , 0 , 0
       0     .06       0   283.9    .045       0   303.4      .1       0
Bank Sta=283.9,303.4
XS Rating Curve= 0 ,0
Exp/Cntr=0.3,0.1

Type RM Length L Ch R = 1 ,1729.6  ,218.3,224.4,230.5
XS GIS Cut Line= 3
      1490800.83      287556.976     1490605.517      287416.351
     1490148.486      287491.872
#Sta/Elev= 30
       0  819.71     9.6  815.86    19.2  813.16    28.9  811.85    38.5  810.23
    48.1  807.91      77  800.03    96.3  793.83   105.9  791.12   115.5  789.34
   125.2  788.56   240.7  782.03   288.9  779.02   327.5  777.15   366.1  776.38
   375.8  775.59   385.4  774.14   395.1  773.31   404.9774.7512   414.4  778.61
   443.3  794.49   462.6  804.63   472.3  809.52   481.9  814.21   501.2  822.89
   530.2  834.57   568.8  849.12   655.6  882.95   684.6  893.88   703.9  900.68
#Mann= 3 , 0 , 0
       0     .06       0   375.8    .045       0   404.9      .1       0
Bank Sta=375.8,404.9
XS Rating Curve= 0 ,0
Exp/Cntr=0.3,0.1

Type RM Length L Ch R = 1 ,1505.1  ,298.6,307.6,316.6
XS GIS Cut Line= 2
     1490755.257      287244.476     1490201.871      287200.206
#Sta/Elev= 30
       0  801.49    29.2  792.83      39  790.17    48.7  787.89    58.4   786.2
    68.2  785.08   116.9  781.54   146.1   778.7   155.8  778.17   194.8  776.19
   214.3  775.54   282.4  774.85   301.9  772.86   311.7  772.62   321.4  773.47
   340.9   776.3   350.6  778.38   360.4  781.41   370.1  785.06   399.3  796.98
   409.1   800.7   428.5  807.16   438.3  809.96     448  812.47   467.5  816.66
   477.2  818.19   506.5  821.33   516.2  823.48   525.9  826.72   555.2  837.26
#Mann= 3 , 0 , 0
       0     .06       0   301.9    .045       0   321.4     .08       0
Bank Sta=301.9,321.4
XS Rating Curve= 0 ,0
Exp/Cntr=0.3,0.1

Type RM Length L Ch R = 1 ,1197.6  ,243.5,249.9,255.9
XS GIS Cut Line= 4
     1490916.715      287098.643     1490725.309      287063.487
      1490332.08      286889.008     1490010.465      286878.591
#Sta/Elev= 30
       0  860.39    19.5  854.06    38.9  846.06    58.4  835.27    87.6  816.62
    97.3   812.1   116.8  807.52   184.9  783.52   204.4  778.42   311.9  771.02
   380.4  770.67   478.2  771.97   487.9  771.06   507.5  769.13   517.8770.1591
   536.8  774.86   575.9  781.95     615  792.68   634.6  795.86   663.8  796.36
   693.1  805.55   702.8  807.49   712.6  805.87   732.1  796.47   741.8  794.34
   819.8     800   829.6  801.73   849.1     808   897.8  828.41   946.6  841.56
#Mann= 3 , 0 , 0
       0     .06       0   487.9    .045       0   517.8     .06       0
Bank Sta=487.9,517.8
XS Rating Curve= 0 ,0
Exp/Cntr=0.3,0.1

Type RM Length L Ch R = 1 ,947.7   ,155.7,148.1,140.3
XS GIS Cut Line= 3
     1490944.059      286826.508     1490692.757      286826.508
     1490298.226      286523.122
#Sta/Elev= 30
       0   858.4      29  848.98      58  836.22    67.7     831    77.3   824.9
    96.7  810.48   106.3  804.86   135.3  796.72   183.6  778.64   193.3  775.82
     203  774.43   212.6  773.94   339.1  770.41  354.97768.9529   368.4  768.06
  374.46768.8153   387.9  771.56   397.7  772.72   436.7  773.95   475.8  778.28
   514.8  779.09   573.3  781.85   612.4  785.05   631.9     789   651.4  796.05
   661.2  798.02   690.4  799.87   700.2  802.21     710  805.97     749   824.1
#Mann= 3 , 0 , 0
       0     .06       0  354.97    .045       0  374.46     .06       0
Bank Sta=354.97,374.46
XS Rating Curve= 0 ,0
Exp/Cntr=0.3,0.1

Type RM Length L Ch R = 1 ,799.6   ,232.6,235.2,237.1
XS GIS Cut Line= 4
     1491107.253      286724.034     1490807.774      286686.273
      1490519.58      286580.414     1490299.528      286476.247
#Sta/Elev= 30
       0  886.57    29.2  873.91    48.7  867.29    68.2  862.47   116.8  851.94
     185  835.02   204.5   829.6     224  821.76   243.4  810.55   253.2  805.91
   272.6   801.1   330.6  777.38   340.2  774.25   349.8  772.46  412.33767.1741
   426.6  766.67   436.2  766.91   551.3  771.29   580.1  774.58   608.9  776.36
   686.8  784.21     716  789.55     755  795.29   774.4  799.06   784.2  801.64
   793.9  805.55   813.4  816.07   823.1  819.72   832.9  822.06   852.3  825.54
#Mann= 3 , 0 , 0
       0     .06       0  412.33    .045       0   436.2     .06       0
Bank Sta=412.33,436.2
XS Rating Curve= 0 ,0
Exp/Cntr=0.3,0.1

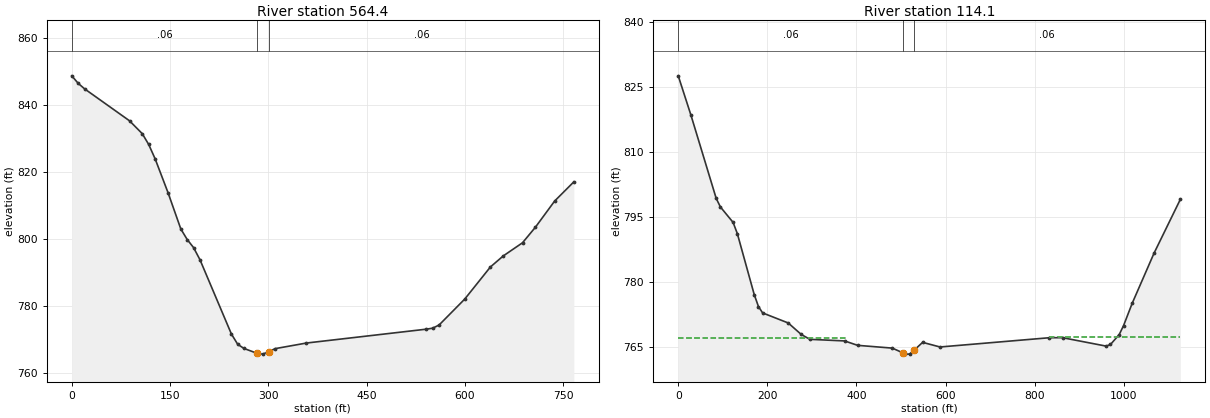
Type RM Length L Ch R = 1 ,564.4   ,457.7,450.3,443.8
XS GIS Cut Line= 4
     1491085.986      286550.466     1490891.976      286482.758
     1490641.976      286364.268     1490358.121      286373.383
#Sta/Elev= 30
       0  848.78     9.8  846.54    19.6  844.89    88.1  835.37   107.6  831.52
   117.4   828.3   127.2  824.02   146.8  813.97   166.4   803.1   176.1  799.96
   185.9  797.53   195.7  793.89   243.6  771.76   253.2   768.7   262.7  767.47
   282.5766.0303   291.4  765.77   300.9  766.53   310.4  767.41   358.1  769.08
   540.9  773.21   550.7  773.51   560.5  774.46   599.7  782.21   638.8  791.77
   658.4  795.06   687.8  798.99   707.4  803.61   736.8  811.43   766.1  817.16
#Mann= 3 , 0 , 0
       0     .06       0   282.5    .045       0   300.9     .06       0
Bank Sta=282.5,300.9
XS Rating Curve= 0 ,0
Exp/Cntr=0.3,0.1

Type RM Length L Ch R = 1 ,114.1   ,113.7,114.1,114.6
XS GIS Cut Line= 5
     1491258.295      286295.648     1491184.076      286080.805
     1490681.472      286022.211     1490592.496      286010.101
     1490400.222      286244.867
#Sta/Elev= 30
       0  827.61    28.4  818.56    85.2  799.28    94.7   797.3   123.1  793.74
   132.6  791.15   170.5  777.07     180  774.29   189.4  772.82   246.8   770.5
     276  767.85   295.4  766.72   373.3  766.35   402.5  765.33   480.3  764.69
   504.7763.5719   509.5   763.3   519.2  763.31     529  764.18   548.4  766.02
   587.4  764.95   832.9  767.09   862.3   767.1   960.2  765.15   969.9  765.53
   989.5  767.82   999.3   769.9  1018.9  775.11  1067.8  786.66  1126.6  799.05
#Mann= 3 , 0 , 0
       0     .06       0   504.7    .045       0     529     .06       0
#XS Ineff= 2 , 0
           373.1  767.13   833.9          767.23
Permanent Ineff=
       F       F
Bank Sta=504.7,529
XS Rating Curve= 0 ,0
Exp/Cntr=0.3,0.1

Chan Stop Cuts=-1
Use User Specified Reach Order=0
Composite Channel Slope=5